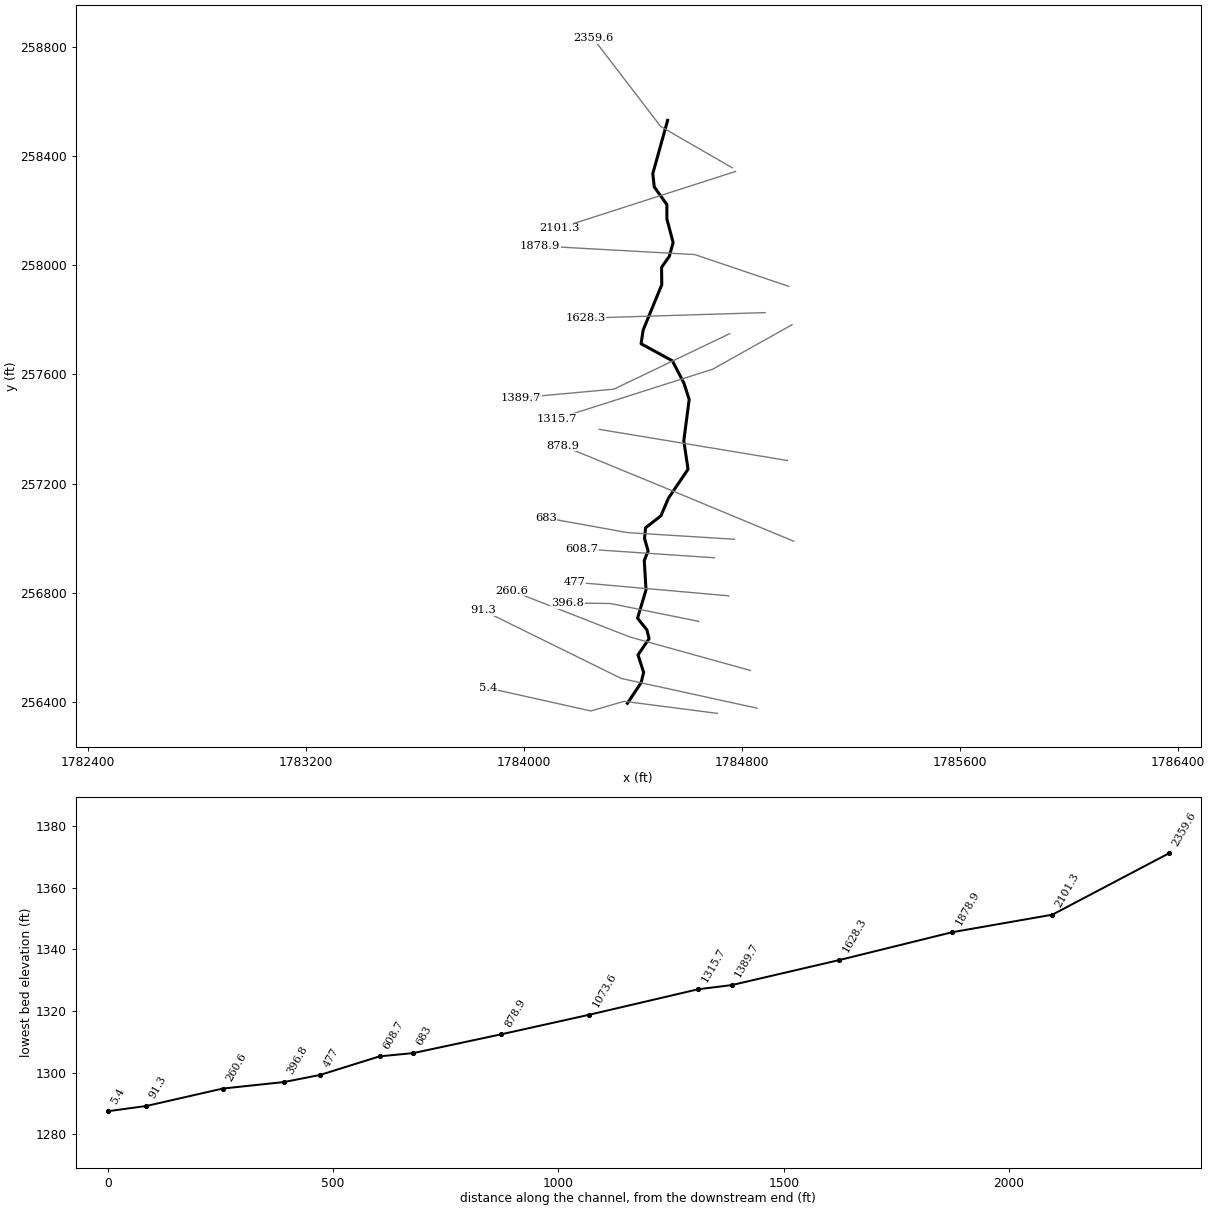
--- DryBr.prj (project) ---

Proj Title=DryBr
Current Plan=p01
Default Exp/Contr=0,0
English Units
Geom File=g01
Flow File=f01
Plan File=p01
BEGIN DESCRIPTION:
END DESCRIPTION:
DSS Export Rating Curves= 0
DSS Export Rating Curve Sorted= 0
DSS Export Volume Flow Curves= 0
DXF OffsetX= 0
DXF OffsetY= 0
DXF ScaleX= 0
DXF ScaleY= 0

--- DryBr.p01 (plan) ---

Plan Title=Floodplain
Program Version=4.00
Geom File=g01
Flow File=f01
K Sum by GR=0
Std Step Tol=0.01
Critical Tol=0.01
Num of Std Step Trials=20
Max Error Tol=0.3
Flow Tol Ratio=0.001
Split Flow NTrial=30
Split Flow Tol=0.02
Split Flow Ratio=0.02
Log Output Level=0
Friction Slope Method=1
Unsteady Friction Slope Method=2
Unsteady Bridges Friction Slope Method=1
Global Log Level=0
CheckData=False
Run HTab=0
Run UNet=0
Run PostProcess=0
UNET Theta=0
UNET Theta Warmup=0
UNET ZTol=0
UNET ZSATol=0
UNET MxIter=0
UNET MaxInSteps=0
UNET DtIC=0
UNET DtMin=0
UNET MaxCRTS=0
UNET WFStab=0
UNET SFStab=0
UNET WFX=0
UNET SFX=0
UNET DSS MLevel=0
UNET DZMax Abort=0
UNET Convert EG Bridges=0
UNET Use Existing IB Tables=0
UNET Froude Limit=0
UNET Froude Power=0
Write IC File=0
Echo Input=False
Echo Output=False
Write Detailed=0

--- DryBr.f01 (steady flow) ---

Flow Title=NFF Regression Equation
Program Version=4.00
Number of Profiles=1
Profile Names=P100yr
River Rch & RM=DryBr,Main      ,2359.6
485.6215
River Rch & RM=DryBr,Main      ,2101.3
717.8183
River Rch & RM=DryBr,Main      ,260.6
773.6345
River Rch & RM=DryBr,Main      ,260.6
818.3038
Boundary for River Rch & Prof#=DryBr,Main      ,1
Up Type=0
Dn Type=3
Dn Slope=0.022955

--- DryBr.g01 (geometry) ---

Geom Title=USGS 10m DEM
Program Version=4.00

River Reach=DryBr           ,Main
Reach XY= 30
     1784526.667      258529.939     1784472.331      258335.095
      1784477.69      258286.376     1784523.974      258221.579
     1784523.974      258169.449     1784546.872      258082.729
     1784532.743       258032.06     1784504.486      257992.111
     1784505.254      257928.443     1784437.124      257762.983
     1784429.337      257712.372     1784544.436      257649.613
     1784586.821      257567.277     1784605.822      257508.327
     1784586.038      257357.119     1784601.611      257252.977
     1784529.587      257146.888     1784502.334       257082.65
     1784445.883      257038.852      1784441.99       256999.92
     1784455.196      256953.677     1784441.031      256918.646
     1784447.432      256811.331     1784416.375      256707.807
     1784450.883      256664.672     1784458.647      256632.752
       1784418.1      256573.226     1784438.805      256509.386
     1784429.315      256471.427     1784379.279      256396.372

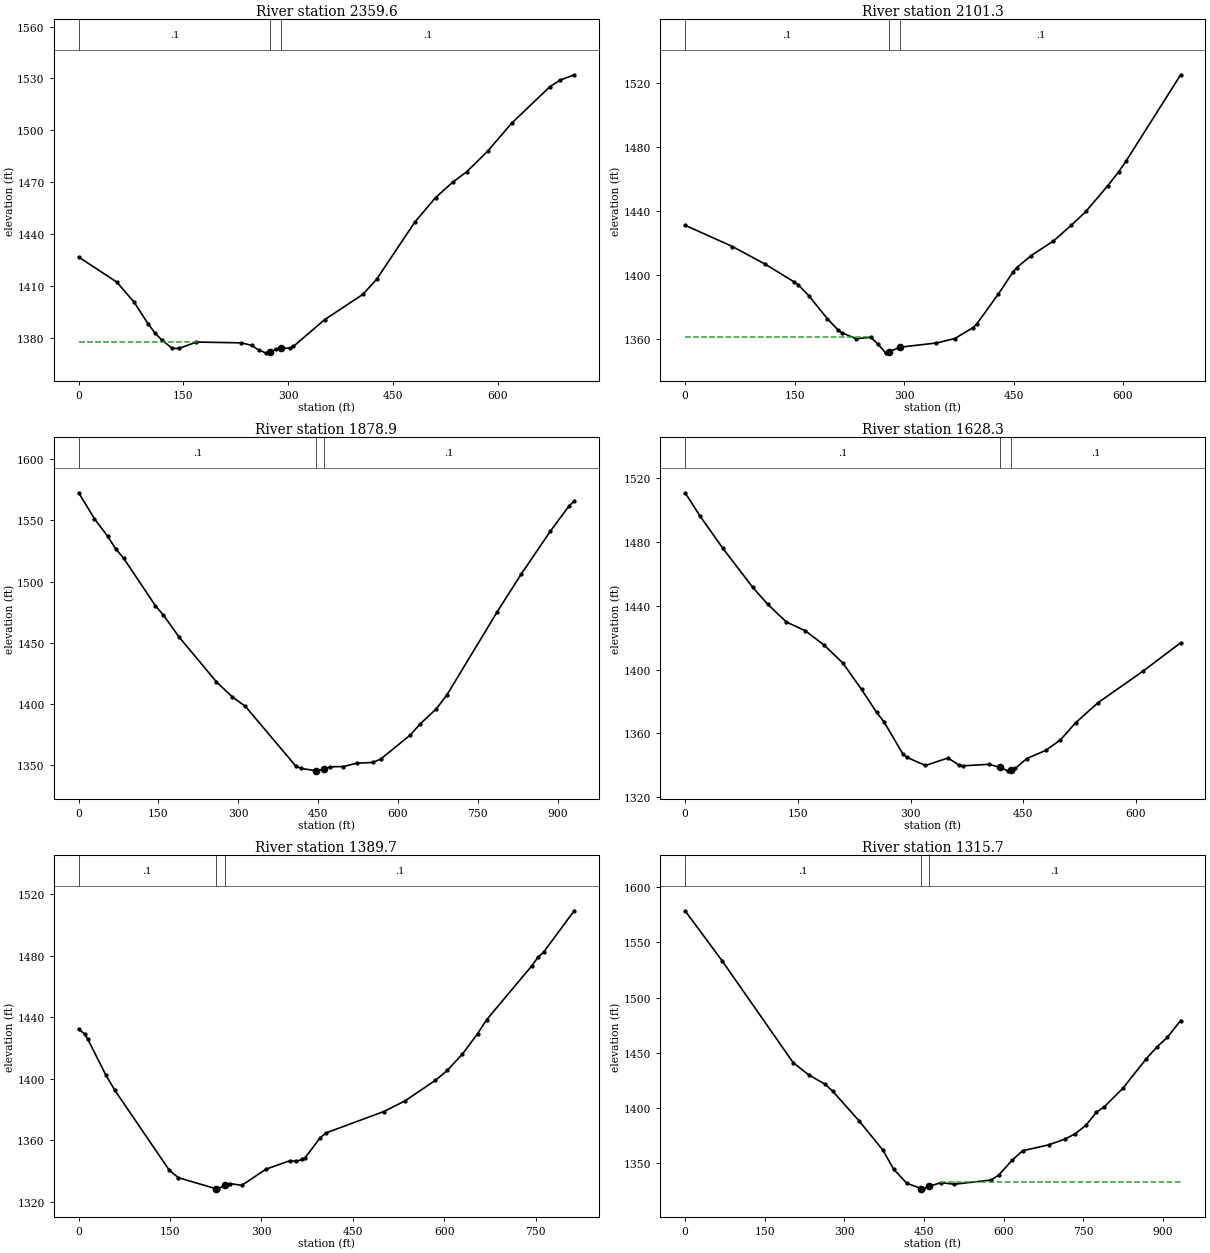
Type RM Length L Ch R = 1 ,2359.6  ,239,258.3,278.9
XS GIS Cut Line= 3
     1784763.197      258356.619     1784501.308       258507.65
     1784253.622      258830.266
#Sta/Elev= 30
       0 1426.67    54.5 1412.19    79.3 1400.56    99.1 1388.17     109 1382.79
     119 1378.63   133.8 1373.79   143.7 1373.72   168.5 1377.44   232.9 1376.97
   247.8 1375.51   257.7 1372.75   267.6 1371.19   274.1 1371.47   282.5 1373.29
   289.1 1373.74   302.3 1373.99   307.3 1374.91   351.9 1390.37   406.5 1404.99
   426.3 1413.74   480.9 1446.79   510.6 1461.02   535.4 1470.03   555.3 1476.02
     585 1487.85   619.8 1504.23   674.3 1525.27   689.2 1529.08     709 1532.15
#Mann= 3 , 0 , 0
       0      .1       0   274.1    .045       0   289.1      .1       0
#XS Ineff= 2 , 0
           174.2 1377.53
Permanent Ineff=
       F       F
Bank Sta=274.1,289.1
XS Rating Curve= 0 ,0
Exp/Cntr=0.3,0.1

Type RM Length L Ch R = 1 ,2101.3  ,230.9,222.4,213.9
XS GIS Cut Line= 2
     1784775.718      258342.945     1784129.295      258135.475
#Sta/Elev= 30
       0 1431.03    64.9 1417.71   109.8 1406.68   149.8 1395.49   154.8 1393.86
   169.7 1386.88   194.7  1372.7   209.7 1365.49   214.6 1363.84   234.6 1360.12
   254.6 1360.98   264.6 1356.59   274.6 1351.28   279.9 1352.04   294.9 1354.84
   344.4 1357.44   369.4 1360.19   394.4 1367.03   399.4 1369.22   429.3 1388.12
   449.3 1401.84   454.3  1404.5   474.2  1412.1   504.2 1421.02   529.1    1431
   549.1 1439.63   579.1 1455.74     594 1464.43     604 1471.01   678.9 1525.06
#Mann= 3 , 0 , 0
       0      .1       0   279.9    .045       0   294.9      .1       0
#XS Ineff= 2 , 0
          251.52 1361.07
Permanent Ineff=
       F       F
Bank Sta=279.9,294.9
XS Rating Curve= 0 ,0
Exp/Cntr=0.3,0.1

Type RM Length L Ch R = 1 ,1878.9  ,247.1,250.6,253.7
XS GIS Cut Line= 3
     1784970.533      257922.636      1784626.43      258038.735
     1784059.276      258070.205
#Sta/Elev= 30
       0 1572.63    29.8 1551.42    54.7 1536.99    69.6  1526.9    84.6 1519.18
   144.3  1480.4   159.2 1472.84     189 1454.74   258.7 1418.36   288.5 1406.05
   313.4  1398.2     408  1349.5     418 1347.54   446.2 1345.69   447.9 1345.58
   461.2 1347.13   472.8 1348.86   497.7 1349.11   522.6 1351.79   552.5 1352.44
   567.4 1355.11   622.3 1374.48   642.2 1384.04   672.1 1396.17     692 1407.51
   786.7 1475.49   831.5 1506.11   886.3 1541.12   921.2 1561.69   931.2 1565.78
#Mann= 3 , 0 , 0
       0      .1       0   446.2    .045       0   461.2      .1       0
Bank Sta=446.2,461.2
XS Rating Curve= 0 ,0
Exp/Cntr=0.3,0.1

Type RM Length L Ch R = 1 ,1628.3  ,227.2,238.6,248.3
XS GIS Cut Line= 2
     1784884.629      257826.316     1784225.397      257806.172
#Sta/Elev= 30
       0 1511.03      20 1496.36      50 1476.34    89.9 1451.76   109.9  1441.1
   134.9 1429.88   159.9 1424.48   184.9  1415.5   209.8 1404.26   234.8 1387.63
   254.8 1373.28   264.8 1367.21   289.8 1347.16   294.8 1345.08   319.8  1339.9
   349.8 1344.58   364.8 1340.12   369.7 1339.68   404.7 1340.64   418.8 1338.68
   429.7 1336.53   433.8 1336.82   439.7 1338.12   454.7 1344.26   479.7  1349.3
   499.6 1355.97   519.6 1366.65   549.6  1379.3   609.6 1399.14   659.5 1416.89
#Mann= 3 , 0 , 0
       0      .1       0   418.8    .045       0   433.8      .1       0
#XS Ineff= 2 , 0
          349.82 1344.43
Permanent Ineff=
       F       F
Bank Sta=418.8,433.8
XS Rating Curve= 0 ,0
Exp/Cntr=0.3,0.1

Type RM Length L Ch R = 1 ,1389.7  ,77.2,74,71.6
XS GIS Cut Line= 3
     1784754.614      257749.405     1784329.776      257546.142
     1783989.173      257515.012
#Sta/Elev= 30
       0 1432.34     9.9 1429.05    14.9 1425.79    44.6 1402.44    59.5 1392.43
   148.7 1340.53   163.6 1335.68   225.1 1328.47     228  1328.4   240.1 1330.65
   247.9 1331.83   267.7 1330.69   307.4 1341.18     347 1346.75   356.9 1346.29
   366.8 1347.54   371.8 1348.75   396.6 1361.77   406.5 1364.85   500.7 1378.68
   535.4 1385.57     585 1398.86   604.8 1405.37   629.6 1416.03   654.4 1429.17
   669.2 1438.28   743.6 1473.44   753.5 1478.89   763.4 1482.59     813 1509.19
#Mann= 3 , 0 , 0
       0      .1       0   225.1    .045       0   240.1      .1       0
Bank Sta=225.1,240.1
XS Rating Curve= 0 ,0
Exp/Cntr=0.3,0.1

Type RM Length L Ch R = 1 ,1315.7  ,253.2,242.2,231.1
XS GIS Cut Line= 3
     1784983.115      257781.905     1784692.353       257619.39
     1784120.258      257437.529
#Sta/Elev= 30
       0 1578.59    69.6  1533.4   203.8 1441.05   233.7 1429.88   263.5 1421.76
   278.4 1415.19   328.1 1388.38   372.8 1361.96   392.6 1344.97   417.4 1332.18
   444.7 1327.27   447.2 1327.06   459.7 1329.35   481.9 1332.66   506.7 1331.21
   576.2    1335   591.1 1339.66   615.9  1352.9   635.7  1361.5   685.3 1366.91
   715.1 1371.98     735 1376.91   754.8 1384.48   774.6 1396.23   789.5 1401.24
   824.3 1417.89   868.9 1444.87   888.8 1455.45   908.6 1464.18   933.4 1479.29
#Mann= 3 , 0 , 0
       0      .1       0   444.7    .045       0   459.7      .1       0
#XS Ineff= 2 , 0
                          481.39         1332.82
Permanent Ineff=
       F       F
Bank Sta=444.7,459.7
XS Rating Curve= 0 ,0
Exp/Cntr=0.3,0.1

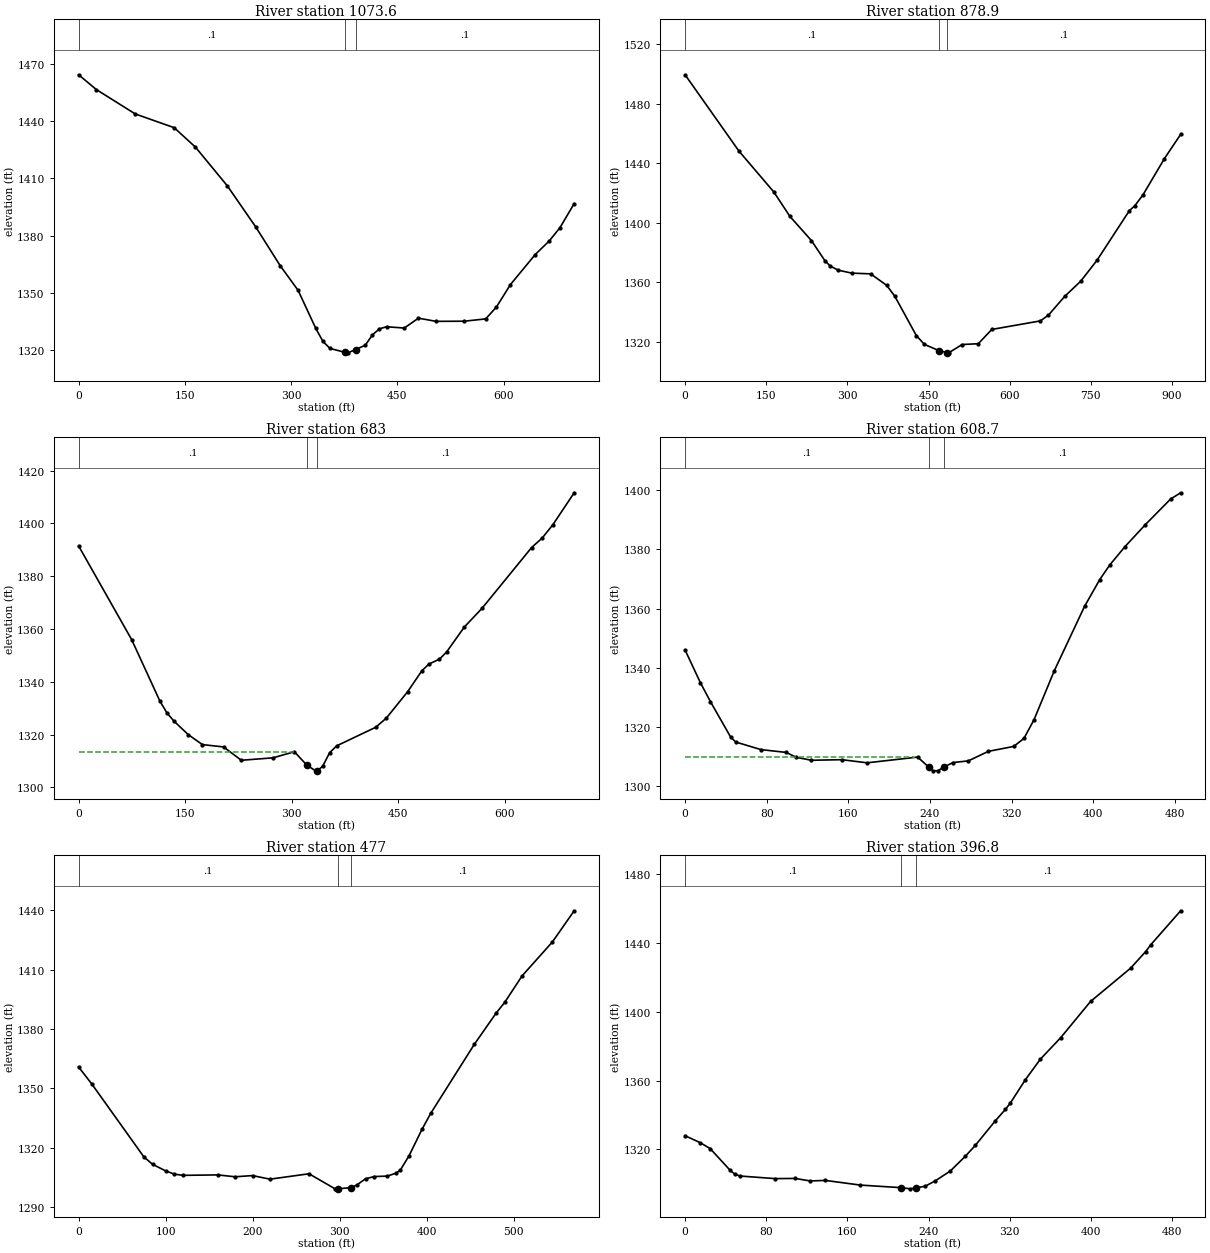
Type RM Length L Ch R = 1 ,1073.6  ,199.5,194.6,189.8
XS GIS Cut Line= 2
     1784966.015      257284.993     1784275.857      257398.934
#Sta/Elev= 30
       0 1464.11      25 1456.39    79.9 1443.64   134.9 1436.45   164.9 1426.29
   209.8  1406.1   249.8 1384.69   284.8 1364.16   309.8 1351.44   334.8  1331.5
   344.8 1324.77   354.8 1321.07   376.1    1319   379.7 1318.76   391.1 1320.45
   404.7 1322.78   414.7 1328.14   424.7 1331.33   434.7 1332.39   459.7 1331.73
   479.7 1336.89   504.6 1335.22   544.6  1335.3   574.6 1336.51   589.6 1342.64
   609.6 1354.48   644.5 1370.13   664.5 1377.33   679.5 1384.22   699.5 1396.78
#Mann= 3 , 0 , 0
       0      .1       0   376.1    .045       0   391.1      .1       0
Bank Sta=376.1,391.1
XS Rating Curve= 0 ,0
Exp/Cntr=0.3,0.1

Type RM Length L Ch R = 1 ,878.9   ,188.4,195.9,203.4
XS GIS Cut Line= 3
     1784989.197      256989.526     1784562.269      257166.478
     1784142.551      257338.861
#Sta/Elev= 30
       0 1499.31    99.4 1448.08     164 1420.56   193.8 1404.09   233.6 1387.84
   258.4 1374.35   268.3 1370.74   283.2 1367.97   308.1    1366   342.9 1365.52
   372.7 1357.76   387.6 1350.48   427.4 1324.02   442.3 1318.11   469.1 1313.92
   484.1 1312.62   487.1 1312.43     512 1318.02   541.9 1318.56   566.9 1328.16
   656.6 1333.89   671.6 1337.78   701.5 1350.32   731.4 1360.64   761.3 1374.62
   821.2 1408.03   831.1 1411.23   846.1  1418.5     886 1443.03   915.9 1459.22
#Mann= 3 , 0 , 0
       0      .1       0   469.1    .045       0   484.1      .1       0
Bank Sta=469.1,484.1
XS Rating Curve= 0 ,0
Exp/Cntr=0.3,0.1

Type RM Length L Ch R = 1 ,683     ,74.6,74.3,74.1
XS GIS Cut Line= 3
     1784771.613      256996.759     1784379.061      257021.099
     1784079.604      257075.141
#Sta/Elev= 30
       0 1391.45    74.7 1355.96   114.5 1332.65   124.5 1328.16   134.4 1325.08
   154.3 1320.02   174.2 1316.24   204.1 1315.35     229  1310.3   273.8 1311.23
   303.7 1313.54     321 1308.53   333.6  1306.3     336 1306.37   343.5 1308.01
   353.5 1313.22   363.4 1315.78   418.2 1322.79   433.2 1326.28   463.1 1336.24
   483.1 1344.16   493.1 1346.73     508 1348.59     518  1351.3     543 1360.76
   567.9 1367.85   637.7 1390.86   652.7 1394.49   667.7 1399.53   697.6 1411.59
#Mann= 3 , 0 , 0
       0      .1       0     321    .045       0     336      .1       0
#XS Ineff= 2 , 0
          302.79 1313.58
Permanent Ineff=
       F       F
Bank Sta=321,336
XS Rating Curve= 0 ,0
Exp/Cntr=0.3,0.1

Type RM Length L Ch R = 1 ,608.7   ,132.2,131.7,131.2
XS GIS Cut Line= 2
     1784698.117      256928.877     1784213.375      256961.554
#Sta/Elev= 30
       0 1346.02    14.9 1335.06    24.8 1328.63    44.6 1316.68    49.6 1314.98
    74.4 1312.42    99.2 1311.47   109.1  1309.8   123.9 1308.83   153.7 1309.02
   178.5 1307.97     228  1309.9   239.2 1306.41   242.9 1305.26   247.9  1305.3
   254.2 1306.66   262.8 1308.06   277.6 1308.62   297.4 1311.84   322.2  1313.5
   332.2  1316.2   342.1 1322.53   361.9 1338.99   391.6 1360.74   406.5 1369.78
   416.4 1374.74   431.3 1380.92   451.1 1388.27   475.9 1396.93   485.8 1399.06
#Mann= 3 , 0 , 0
       0      .1       0   239.2    .045       0   254.2      .1       0
#XS Ineff= 2 , 0
          223.94 1309.99
Permanent Ineff=
       F       F
Bank Sta=239.2,254.2
XS Rating Curve= 0 ,0
Exp/Cntr=0.3,0.1

Type RM Length L Ch R = 1 ,477     ,82.7,80.2,77.6
XS GIS Cut Line= 2
     1784751.647      256789.588     1784184.212      256839.569
#Sta/Elev= 30
       0 1360.79      15 1352.31      75 1315.37      85 1311.63    99.9 1308.33
   109.9 1306.67   119.9 1306.05   159.9 1306.27   179.9 1305.33   199.9 1305.93
   219.9 1304.12   264.8 1306.84   294.8 1299.23   297.9 1299.23   312.9 1299.84
   319.8 1301.17   329.8 1304.33   339.8 1305.44   354.8 1305.68   364.8 1307.14
   369.8 1308.71   379.8 1315.94   394.7 1329.32   404.7 1337.37   454.7 1372.19
   479.7 1387.94   489.7 1393.45   509.7 1406.85   544.6 1424.03   569.6 1439.77
#Mann= 3 , 0 , 0
       0      .1       0   297.9    .045       0   312.9      .1       0
Bank Sta=297.9,312.9
XS Rating Curve= 0 ,0
Exp/Cntr=0.3,0.1

Type RM Length L Ch R = 1 ,396.8   ,137.4,136.2,135.8
XS GIS Cut Line= 3
     1784641.416      256695.978     1784317.368      256761.477
     1784159.464      256763.403
#Sta/Elev= 30
       0 1327.84    14.8 1323.82    24.7 1320.36    44.4 1307.71    49.3  1305.3
    54.3 1304.37    88.8 1302.86   108.6 1302.97   123.4 1301.49   138.2 1301.82
   172.7  1299.1   212.5 1297.61     222 1296.91   227.5 1297.42   236.8 1298.48
   246.7 1301.58   261.5 1307.33   276.3 1315.91   286.2 1322.29   305.9 1336.59
   315.8 1343.19   320.7 1346.94   335.5  1360.5   350.3 1372.48   370.1 1384.83
   399.7 1406.03   439.2 1425.43     454 1435.05   458.9 1438.94   488.5 1458.84
#Mann= 3 , 0 , 0
       0      .1       0   212.5    .045       0   227.5      .1       0
Bank Sta=212.5,227.5
XS Rating Curve= 0 ,0
Exp/Cntr=0.3,0.1

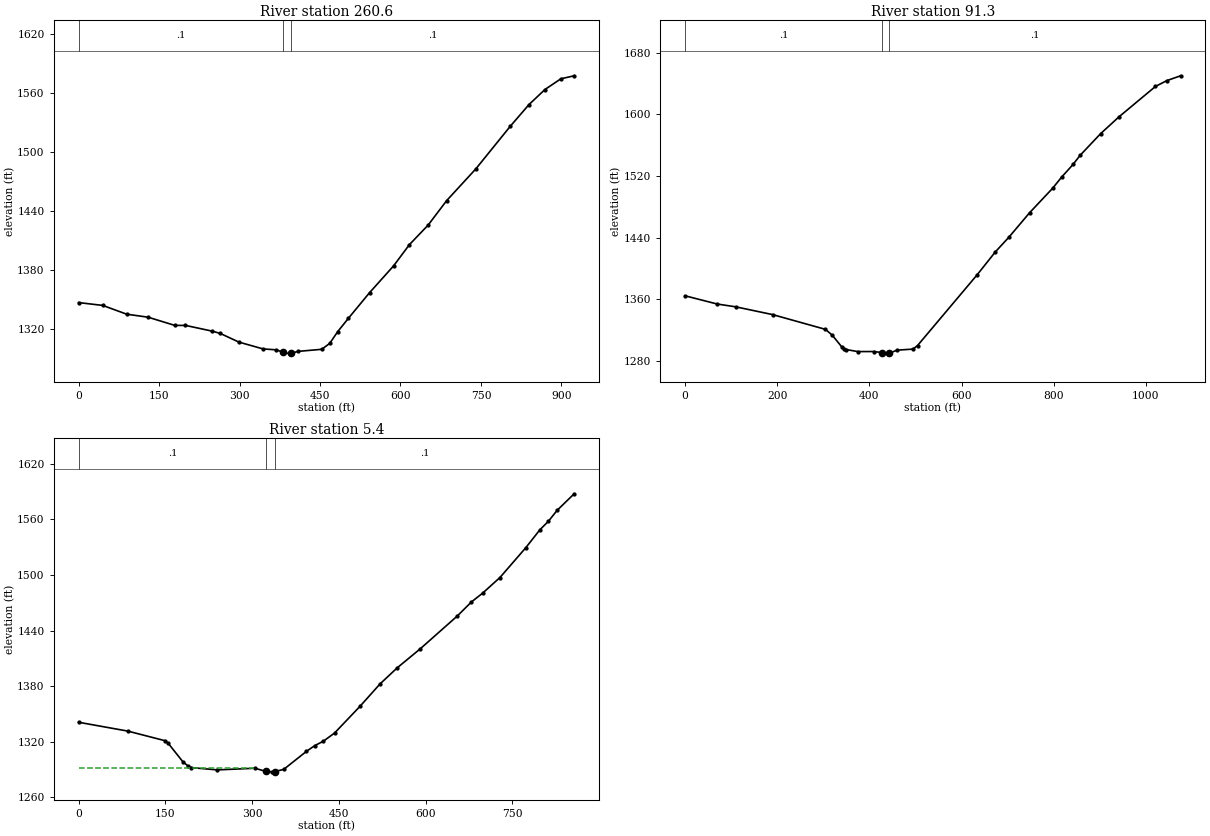
Type RM Length L Ch R = 1 ,260.6   ,168.8,169.4,169.6
XS GIS Cut Line= 3
     1784830.195      256516.507     1784388.618      256638.833
     1783954.855      256808.041
#Sta/Elev= 30
       0 1346.92    44.8 1344.06    89.6 1335.12   129.5 1332.06   179.3 1323.72
   199.2 1323.71     249 1317.88     264 1315.56   298.8 1306.72   343.7 1299.82
   368.6 1298.85   381.3 1296.38   393.5 1294.79   396.3 1295.21   408.4 1297.26
   453.2  1299.4   468.1 1305.41     483 1317.38   502.8 1330.87   542.4 1357.04
     587 1384.16   616.7  1405.9   651.4 1425.65     686  1450.6   740.5 1482.96
   804.9  1526.4   839.6 1548.36   869.3 1563.65     899 1574.56   923.8 1577.63
#Mann= 3 , 0 , 0
       0      .1       0   381.3    .045       0   396.3      .1       0
Bank Sta=381.3,396.3
XS Rating Curve= 0 ,0
Exp/Cntr=0.3,0.1

Type RM Length L Ch R = 1 ,91.3    ,82.3,85.8,91.7
XS GIS Cut Line= 3
     1784854.649      256378.448     1784356.836      256487.115
     1783848.744      256736.756
#Sta/Elev= 30
       0 1364.43    69.9 1353.74   109.9 1350.14   189.8 1340.07   304.7 1320.89
   319.7 1313.13   339.7  1298.4   344.7 1295.77   349.7 1294.73   374.7 1292.05
   409.6 1292.12   427.9 1290.74   439.6 1289.13   442.9 1289.64   459.6 1293.89
   494.6 1295.27   504.5 1299.88   633.7 1391.54   673.4 1421.39   703.2 1440.73
   747.9 1472.31   797.6 1503.87   817.4 1518.53   842.2 1534.95   857.2 1546.56
   901.8 1574.75   941.6 1596.58    1021 1636.11  1045.8 1643.71  1075.6 1649.93
#Mann= 3 , 0 , 0
       0      .1       0   427.9    .045       0   442.9      .1       0
Bank Sta=427.9,442.9
XS Rating Curve= 0 ,0
Exp/Cntr=0.3,0.1

Type RM Length L Ch R = 1 ,5.4     ,8.8,5.4,0
XS GIS Cut Line= 4
      1784709.27      256359.358     1784367.116      256403.412
     1784245.232      256368.169     1783869.303      256451.872
#Sta/Elev= 30
       0 1340.94      85 1331.41     150 1320.94     155 1318.14     180 1298.55
     190 1293.28     195 1291.98     240 1289.52     305 1291.32   324.2 1287.81
     335 1287.42   339.2 1287.69   354.7 1290.08   393.8 1309.44   408.4 1315.74
   423.1 1320.43   442.6  1329.3   486.7 1358.22   521.2  1382.3   550.9 1399.68
   590.4 1420.02   654.6  1455.5   679.2 1470.76     699 1480.51   728.6 1497.19
     773 1529.14   797.7 1548.74   812.6 1558.03   827.4 1569.65     857 1587.61
#Mann= 3 , 0 , 0
       0      .1       0   324.2    .045       0   339.2      .1       0
#XS Ineff= 2 , 0
           302.7 1291.35
Permanent Ineff=
       F       F
Bank Sta=324.2,339.2
XS Rating Curve= 0 ,0
Exp/Cntr=0.3,0.1

Chan Stop Cuts=-1
Use User Specified Reach Order=0